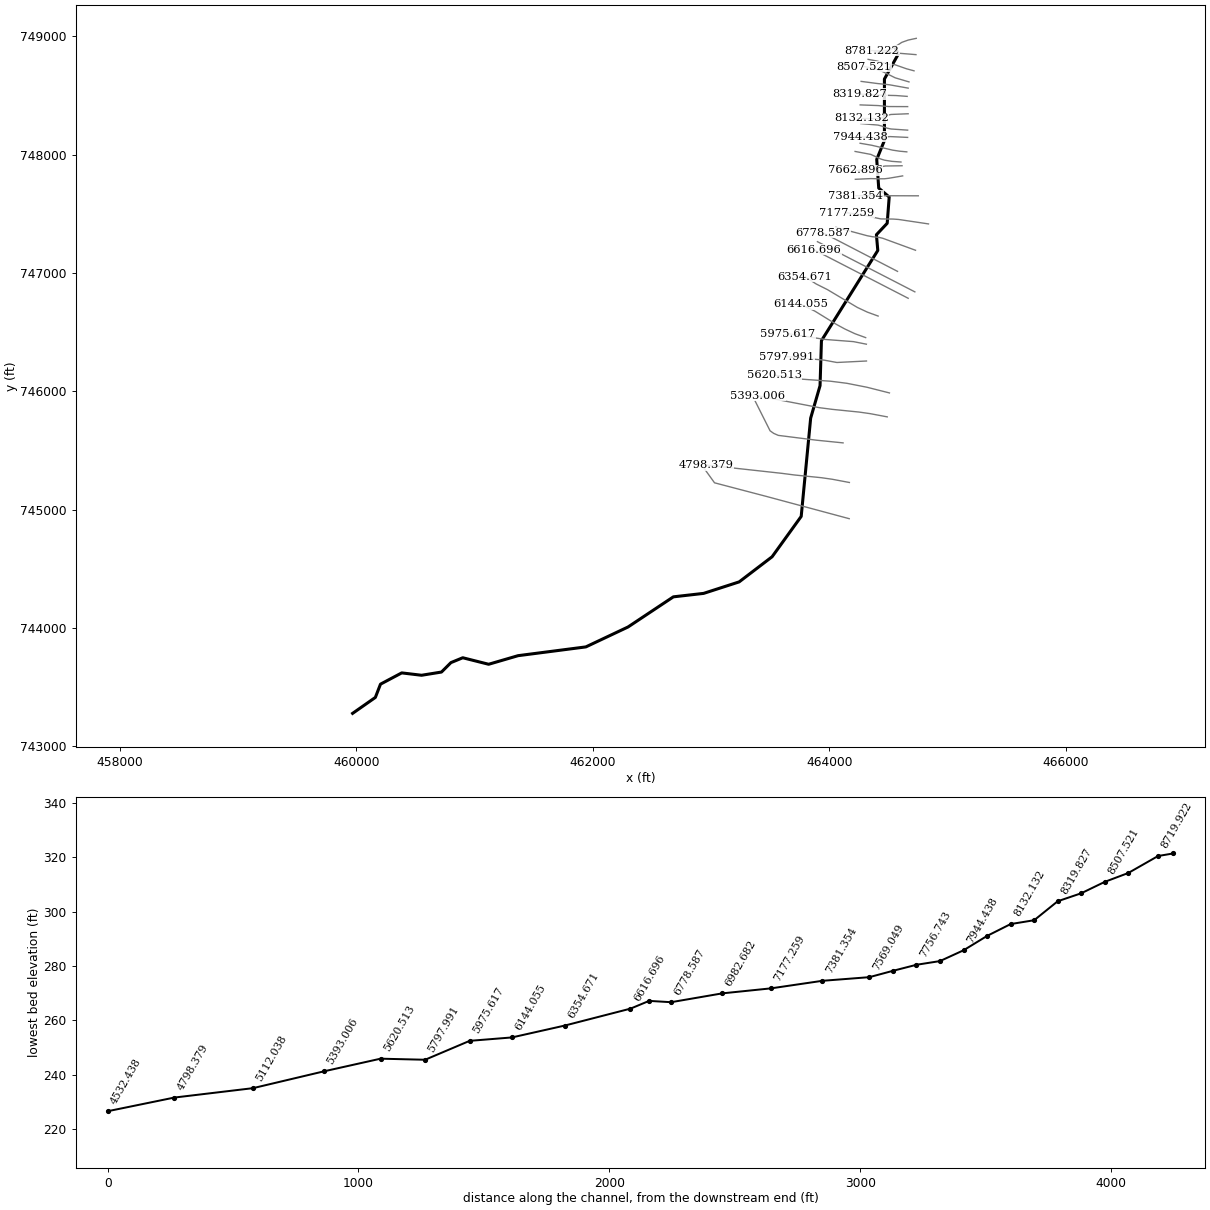
--- 2598_ras.prj (project) ---

Proj Title=2598
Current Plan=p01
Default Exp/Contr=0.3,0.1
English Units
Geom File=g01
Flow File=f01
Plan File=p01
Y Axis Title=Elevation
X Axis Title(PF)=Main Channel Distance
X Axis Title(XS)=Station
BEGIN DESCRIPTION:
RFD model 2598 exported to HEC-RAS
END DESCRIPTION:

--- 2598_ras.p01 (plan) ---

Plan Title=Plan 01
Program Version=4.10
Short Identifier=Plan 01
Geom File=g01
Flow File=f01
Subcritical Flow
Calc Critical at every XS
Secant Critical Depth

--- 2598_ras.f01 (steady flow) ---

Flow Title=Flow 01
Program Version=5.01
Number of Profiles= 6
Profile Names=10yr,25yr,50yr,100yr,100plus,500yr
River Rch & RM=2598,40,8781.222
   96.98  178.07  262.87  353.24  515.73 1118.28
River Rch & RM=2598,40,7381.354
   97.69  179.38  264.81  355.87  519.56 1125.52
River Rch & RM=2598,40,7177.259
  102.95  189.21  279.49  375.76  548.61 1180.49
River Rch & RM=2598,40,6982.682
  104.96  192.98  285.14  383.43  559.81 1201.72
River Rch & RM=2598,40,6778.587
  106.91  196.66  290.67  390.99  570.85 1222.81
River Rch & RM=2598,40,6691.027
  114.25  210.49  311.48  419.37  612.27 1301.22
River Rch & RM=2598,40,6616.696
   122.8   226.6  335.67  452.33   660.4 1391.17
River Rch & RM=2598,40,6354.671
  124.89  230.55  341.62  460.46  672.27 1413.29
River Rch & RM=2598,40,6144.055
  127.39  235.28  348.74  470.17  686.45 1439.67
River Rch & RM=2598,40,5975.617
  129.47   239.2  354.64  478.23  698.22  1461.5
River Rch & RM=2598,40,5797.991
  131.33  242.73  359.95  485.47  708.79 1481.05
River Rch & RM=2598,40,5620.513
  132.16  244.29   362.3  488.68  713.48  1489.7
River Rch & RM=2598,40,5393.006
  165.15  306.74  456.45  617.35  901.33 1831.49
River Rch & RM=2598,40,5112.038
  170.59  317.05     472  638.61  932.38 1886.95
River Rch & RM=2598,40,4798.379
  174.23  323.96  482.44   652.9  953.24 1924.22
River Rch & RM=2598,40,4532.438
  181.04  336.92  502.03  679.75  992.44 1994.08
River Rch & RM=2598,40,4006.137
  190.86  355.56  530.19  718.29  1048.7 2093.32
River Rch & RM=2598,40,3550.867
   203.2  378.97  565.53  766.65  1119.3 2216.69
River Rch & RM=2598,40,3227.791
  212.46  396.52  592.04   802.9 1172.23 2308.38
River Rch & RM=2598,40, 2913.94
  220.18  411.16  614.13  833.11 1216.35  2384.3
River Rch & RM=2598,40,2185.055
  227.83  425.67  636.04  863.09 1260.11 2459.29
Boundary for River Rch & Prof#=2598,40,1
Up Type= 0
Dn Type= 2
Boundary for River Rch & Prof#=2598,40,2
Up Type= 0
Dn Type= 2
Boundary for River Rch & Prof#=2598,40,2
Up Type= 0
Dn Type= 2
Boundary for River Rch & Prof#=2598,40,2
Up Type= 0
Dn Type= 2
Boundary for River Rch & Prof#=2598,40,2
Up Type= 0
Dn Type= 2
Boundary for River Rch & Prof#=2598,40,2
Up Type= 0
Dn Type= 2

--- 2598_ras.g01 (geometry) ---

Geom Title=2598
Program Version=4.10

River Reach=2598,40
Reach XY= 30
 464551.51144442748909.205266625 464583.93379314748852.912968886
464465.573944569 748639.67401661464465.573944569748120.142766565
464400.469777733 747959.98651661464417.396861196 747717.79901661
464505.938527882747642.278183267464489.072339237747420.124947414
464397.865611076747323.267766595464409.584361196747190.455266595
463933.021861196746427.434433281463921.303111076746047.226099953
463841.876027733745772.486516625463761.928111225744941.757349953
463515.897139788744600.652696237463237.424917579744388.152696237
462936.730473131744290.930474028462681.174917579744261.763807386
462297.841584444744006.902696267461941.251726478743838.503617302
 461368.30912891743764.350801274461119.334684521743691.669810608
460900.503032297743746.776400268460800.380135506743705.609417692
460720.554817528743625.883867294460552.223948807743598.711950779
460384.424575388743618.755571201460204.797929853743523.399601206
460161.478195459743411.206762075459968.983391047743276.462003946

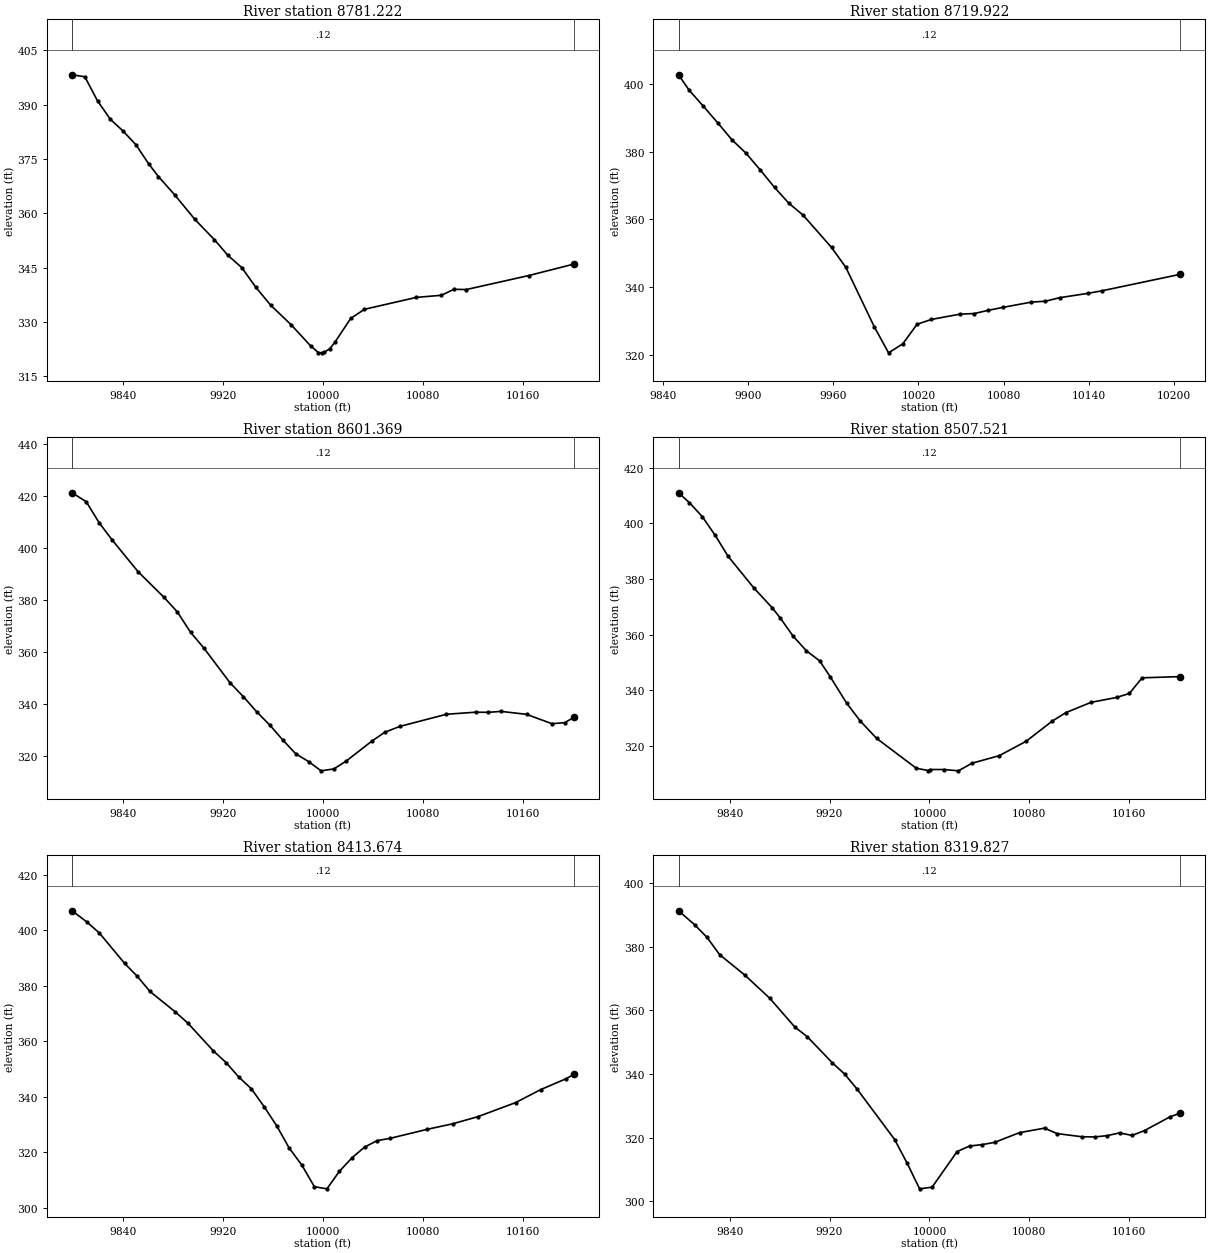
Type RM Length L Ch R = 1 ,8781.222,61.299600,61.299600,61.299600
XS GIS Cut Line= 6
464734.977823644748983.887604628464667.319390821748969.398261812
464612.534373352748949.905754374464513.816694627748884.943029772
464454.743487916748878.253831933464358.961155435748880.187533173
#Sta/Elev= 30
9799.093398.24649809.297397.69549819.524391.0155 9829.75385.95569839.977382.7002
9850.204378.9423 9860.43373.65739868.285 370.1289881.186365.12959897.447358.3062
9913.046352.72539923.825348.41239934.954 345.0149946.198 339.5859958.014334.6742
9974.622329.19159990.056323.41939996.277321.5706    9999321.4878   10001321.6278
10005.42322.6346 10009.4324.359510022.23331.010310033.19333.510110074.71336.7925
10094.74337.376210104.76339.022610114.76338.963210164.77342.828910200.82345.9876
#Mann= 3 , 0 , 0
9799.093    0.12       09799.093    0.12       010200.82    0.12       0
#XS Ineff= 2 , 0
       0                               0
Bank Sta=9799.093,10200.82
Exp/Cntr=0.3,0.1

Type RM Length L Ch R = 1 ,8719.922,118.553600,118.553600,118.553600
XS GIS Cut Line= 4
464732.370950311748846.094276145464546.145949602748861.325148106
 464515.62891981748865.253405228464380.061487138748870.806255817
#Sta/Elev= 27
9851.096402.82289858.492398.29969868.525393.53989878.559388.66349888.592383.6273
9898.625 379.5979908.659374.64589918.692369.48279928.726364.81349938.759 361.296
9958.826351.71439968.859345.84379988.926328.22649998.959320.527310008.99323.2014
10019.03328.973910029.06 330.41210049.18331.972510059.26332.155710068.71333.0679
10079.35333.975710099.37335.533410109.37 335.80310119.38336.8437 10139.4338.1388
10149.41338.905510204.39343.7748
#Mann= 3 , 0 , 0
9851.096    0.12       09851.096    0.12       010204.39    0.12       0
#XS Ineff= 2 , 0
       0                               0
Bank Sta=9851.096,10204.39
Exp/Cntr=0.3,0.1

Type RM Length L Ch R = 1 ,8601.369,93.847200,93.847200,93.847200
XS GIS Cut Line= 6
 464715.93062964748709.225675496 464651.61121813748726.635341238
464553.735831553 748761.02991269464500.295238229748764.743379451
464402.211993085748792.033493184464327.778368328748806.130524828
#Sta/Elev= 30
9799.115421.09719810.439417.68359820.799409.58549831.158403.00349851.878390.8316
9872.756380.91949883.356375.36579893.955367.52379904.555361.50039925.754348.0147
9936.353342.74349946.953336.95999957.552331.80129968.152325.9735 9978.34320.7859
 9988.47317.85089998.496314.278810008.83315.027210018.62318.034510039.23325.7273
10049.61329.117310061.61331.350710098.92336.013610122.27336.8097 10132.5336.7581
10142.68337.113710163.03 335.97810183.39332.387510193.57332.790910200.92334.7878
#Mann= 3 , 0 , 0
9799.115    0.12       09799.115    0.12       010200.92    0.12       0
#XS Ineff= 2 , 0
       0                               0
Bank Sta=9799.115,10200.92
Exp/Cntr=0.3,0.1

Type RM Length L Ch R = 1 ,8507.521,93.847300,93.847300,93.847300
XS GIS Cut Line= 6
464673.381720197748615.508529581 464556.99110111748649.932413641
464455.358126761748700.321787739464413.710946379748716.848799538
464355.875960082748732.971422154 464294.98890179748745.107056096
#Sta/Elev= 30
9799.048411.02289807.704407.49729818.031402.46579828.359395.74919838.686 388.223
9859.342376.79739874.199369.60729880.355366.0751 9890.92359.39379901.484354.1831
9912.048350.57189920.509344.85169933.627335.38949944.567328.94369957.665322.6925
9989.484 311.929    9999311.124110000.78311.474810011.99311.4777 10023.2311.0046
10034.01313.731110055.91316.461810077.43321.630410098.24  328.8610109.17331.9245
10129.38335.631110149.95337.410910160.14338.837510170.34344.468810200.94344.9001
#Mann= 3 , 0 , 0
9799.048    0.12       09799.048    0.12       010200.94    0.12       0
#XS Ineff= 2 , 0
       0                               0
Bank Sta=9799.048,10200.94
Exp/Cntr=0.3,0.1

Type RM Length L Ch R = 1 ,8413.674,93.847300,93.847300,93.847300
XS GIS Cut Line= 6
464666.425269251 748562.96722462464509.206729065748590.925033219
464469.171399107748595.546673129 464467.17485036748595.429229092
464406.186390323748601.835376509464268.690338758748619.868665591
#Sta/Elev= 30
9799.014407.08729810.618403.13939820.775399.12729841.089388.13229851.246383.4649
9861.403377.99089881.716370.61549891.873366.52279912.187 356.5619922.344352.3622
9932.501347.15599942.658342.88089952.815336.47169962.933329.5516    9973321.4706
9983.066315.37839993.133307.573610003.19306.802810013.24313.1651 10023.3318.0179
10033.35321.858410043.41324.194810053.46324.980810083.69328.287410103.86330.2511
10124.03332.819410154.29337.895110174.46 342.59810194.63346.4803   10201348.0996
#Mann= 3 , 0 , 0
9799.014    0.12       09799.014    0.12       0   10201    0.12       0
#XS Ineff= 2 , 0
       0                               0
Bank Sta=9799.014,10201
Exp/Cntr=0.3,0.1

Type RM Length L Ch R = 1 ,8319.827,93.847200,93.847200,93.847200
XS GIS Cut Line= 6
464657.838057959748493.140573276464563.217013866748500.137526747
464458.155151497748502.847552359464456.161042527748503.000945366
464370.282842367748505.800840414464256.443192847748512.927048196
#Sta/Elev= 30
9799.024391.32019811.897386.94019821.924382.92599831.952 377.5179852.006371.1352
9872.061 363.8179892.115354.77799902.123351.7192 9922.13343.53599932.133339.9411
9942.136335.19199972.146319.3737 9982.15311.90669992.153303.857510002.16304.3843
10022.17315.578710032.18317.327610042.18317.764210052.19318.4696 10072.2321.5375
10092.22  322.9510102.24321.239210122.28320.2355 10132.3320.185710142.31320.5843
10152.33321.459410162.35320.651610172.37322.202910192.41326.438510200.99327.7053
#Mann= 3 , 0 , 0
9799.024    0.12       09799.024    0.12       010200.99    0.12       0
#XS Ineff= 2 , 0
       0                               0
Bank Sta=9799.024,10200.99
Exp/Cntr=0.3,0.1

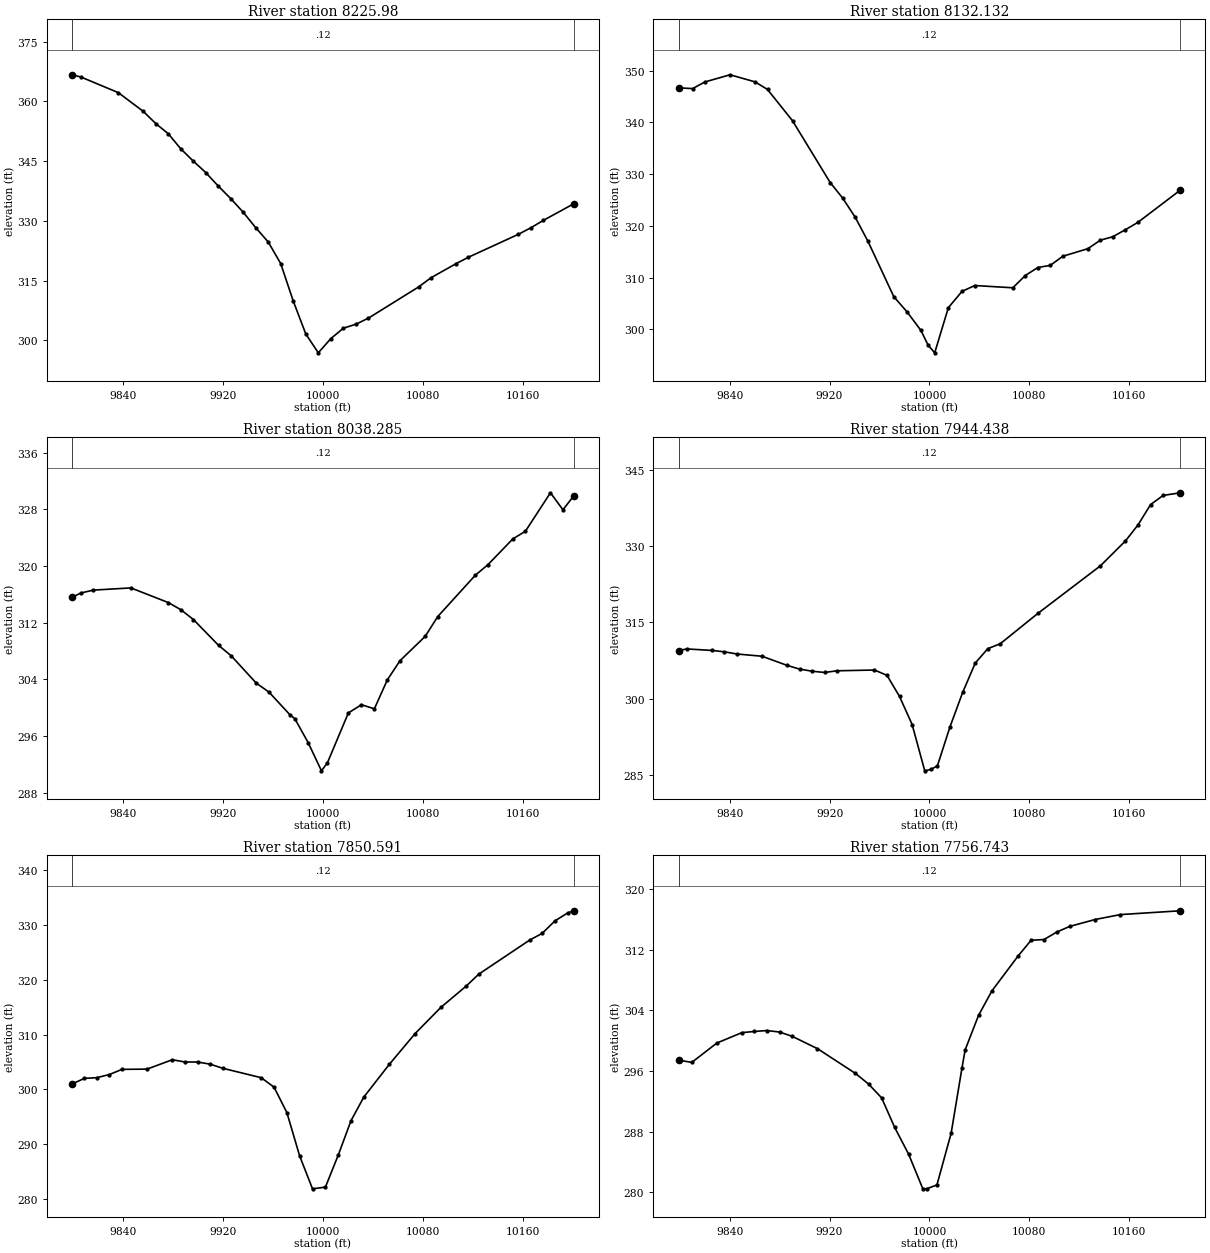
Type RM Length L Ch R = 1 , 8225.98,93.847300,93.847300,93.847300
XS GIS Cut Line= 6
464662.100040191748406.580051231464502.560007007748407.127455768
464462.272685603748410.467485989464460.295942206748410.771600347
464411.776078152748415.479728365 464260.64354528748421.055146945
#Sta/Elev= 30
9799.033366.70959806.134366.14929836.134362.21379856.134 357.4989866.134354.4404
9876.134351.89419886.134348.10259896.134345.02649906.134342.14929916.134338.7579
9926.134335.60899936.134332.18369946.134328.30339956.134324.7257 9966.16319.2897
9976.195309.88599986.229301.62519996.263296.867310006.32300.451210016.37303.0581
10026.41304.054910036.46305.592310076.54313.403310086.55315.727110106.56 319.257
10116.57320.8866 10156.6326.6504 10166.6328.289710176.61330.151810200.98 334.321
#Mann= 3 , 0 , 0
9799.033    0.12       09799.033    0.12       010200.98    0.12       0
#XS Ineff= 2 , 0
       0                               0
Bank Sta=9799.033,10200.98
Exp/Cntr=0.3,0.1

Type RM Length L Ch R = 1 ,8132.132,93.847300,93.847300,93.847300
XS GIS Cut Line= 6
464666.241496316748346.273505967464520.460498993748340.181519932
464490.456822873 748332.41752635464444.961626403748311.711142872
464411.539957598748305.045135516464270.969030209748306.168024564
#Sta/Elev= 30
9799.113346.65369810.354346.50629820.355347.79969840.355349.17569860.355347.8073
9870.356346.33649890.377340.28879920.505  328.369930.547325.3414 9940.59321.6309
9950.789316.99319971.448306.30789982.153303.33879993.172299.7782    9999296.9062
10004.21295.445910015.15304.177610026.09307.325310036.29308.454910066.76308.0159
10076.76 310.38710086.77311.935110096.78312.350310106.78314.107910126.79315.5677
 10136.8317.211710146.81 317.88510156.81 319.22610166.82 320.64510200.87326.8937
#Mann= 3 , 0 , 0
9799.113    0.12       09799.113    0.12       010200.87    0.12       0
#XS Ineff= 2 , 0
       0                               0
Bank Sta=9799.113,10200.87
Exp/Cntr=0.3,0.1

Type RM Length L Ch R = 1 ,8038.285,93.847200,93.847200,93.847200
XS GIS Cut Line= 6
 464662.04055862748207.674317567464521.528783255 748217.38477323
464488.346767763 748224.39456527464441.744091722748242.548752707
464411.712263694748250.383730882464266.284898905748263.195474532
#Sta/Elev= 30
9799.061315.57379806.111  316.199816.125316.59539846.168316.9058 9876.21314.8321
9886.224313.82319896.266312.43879916.358308.79799926.404307.3396 9946.61303.4603
9956.831302.18599973.852298.93699977.428298.45259988.113295.07339998.799291.0781
10003.55292.204810020.36299.254510030.84300.413810041.17299.833710051.51303.9024
10061.68306.621210081.85310.059410091.93312.857710122.03318.695410132.06320.1732
10152.11323.830910162.14324.903610182.19330.337610192.21327.939410200.95329.9214
#Mann= 3 , 0 , 0
9799.061    0.12       09799.061    0.12       010200.95    0.12       0
#XS Ineff= 2 , 0
       0                               0
Bank Sta=9799.061,10200.95
Exp/Cntr=0.3,0.1

Type RM Length L Ch R = 1 ,7944.438,93.847300,93.847300,93.847300
XS GIS Cut Line= 6
464661.755094355748146.246045055464515.859861203748153.137919306
464484.905132181748151.073061438464423.882469022748141.905332341
464390.024229935 748140.66799973464261.315784399 748152.06734582
#Sta/Elev= 30
9799.023309.46059805.789309.77769825.822309.48469835.839309.20799845.856308.7802
9865.889308.34169885.922306.54479895.939305.81229905.953 305.3999915.955305.1423
9925.957305.47559955.985305.62819966.008304.5786 9976.03300.42799986.137294.9006
9996.246285.7839   10001 286.04910006.36286.755310016.47 294.44710026.59301.2045
 10036.7 306.99910046.72309.826710056.73310.801810086.76316.754210136.91 326.128
10157.02331.039610167.08334.193110177.14338.1881 10187.2339.993310200.96340.5143
#Mann= 3 , 0 , 0
9799.023    0.12       09799.023    0.12       010200.96    0.12       0
#XS Ineff= 2 , 0
       0                               0
Bank Sta=9799.023,10200.96
Exp/Cntr=0.3,0.1

Type RM Length L Ch R = 1 ,7850.591,93.847300,93.847300,93.847300
XS GIS Cut Line= 6
464654.794717612748024.077023728464593.872960993748029.724174939
464534.103848983748038.736957343464455.938049867748057.121512329
464357.402530026748080.000978285464260.043841914748096.795853999
#Sta/Elev= 30
 9799.06300.97559808.897301.9998 9818.94302.13459828.983302.70689839.025303.6465
9859.111303.69529879.329305.40669889.442304.99719899.555304.99019909.669304.6002
9919.782303.84649950.565302.12059960.831300.38959971.097 295.7489981.363287.8026
9991.629281.810710001.96282.123610012.23287.9648 10022.5294.288410032.76298.5976
10053.29304.607110073.83 310.19510094.36314.960610114.74318.878610124.89321.0671
10165.48327.268110175.63328.512510185.78330.781710195.92332.236610200.95332.6344
#Mann= 3 , 0 , 0
 9799.06    0.12       0 9799.06    0.12       010200.95    0.12       0
#XS Ineff= 2 , 0
       0                               0
Bank Sta=9799.06,10200.95
Exp/Cntr=0.3,0.1

Type RM Length L Ch R = 1 ,7756.743,93.847200,93.847200,93.847200
XS GIS Cut Line= 6
464605.614945987747938.273967012 464529.06584683747943.706988241
464466.001708853747953.834767311464433.414575109747963.992580309
 464350.63022164748002.526908419464217.535706822748027.536167964
#Sta/Elev= 30
9799.117297.41859809.759297.12819829.809 299.681 9849.86301.05429859.885301.2073
 9869.91301.32899879.977301.13129890.105300.56769910.361298.9387 9940.78295.6725
9951.255294.2725 9961.73292.44989972.204288.54139983.353285.0153 9994.63280.4865
9997.684280.443310006.02280.958110017.41287.785910026.07296.390910028.62298.7829
10039.32303.321310050.01306.552110071.16311.196410081.43  313.24 10091.7313.3349
10101.98314.322410112.25315.0637 10132.7315.980210152.92316.629210200.91317.1309
#Mann= 3 , 0 , 0
9799.117    0.12       09799.117    0.12       010200.91    0.12       0
#XS Ineff= 2 , 0
       0                               0
Bank Sta=9799.117,10200.91
Exp/Cntr=0.3,0.1

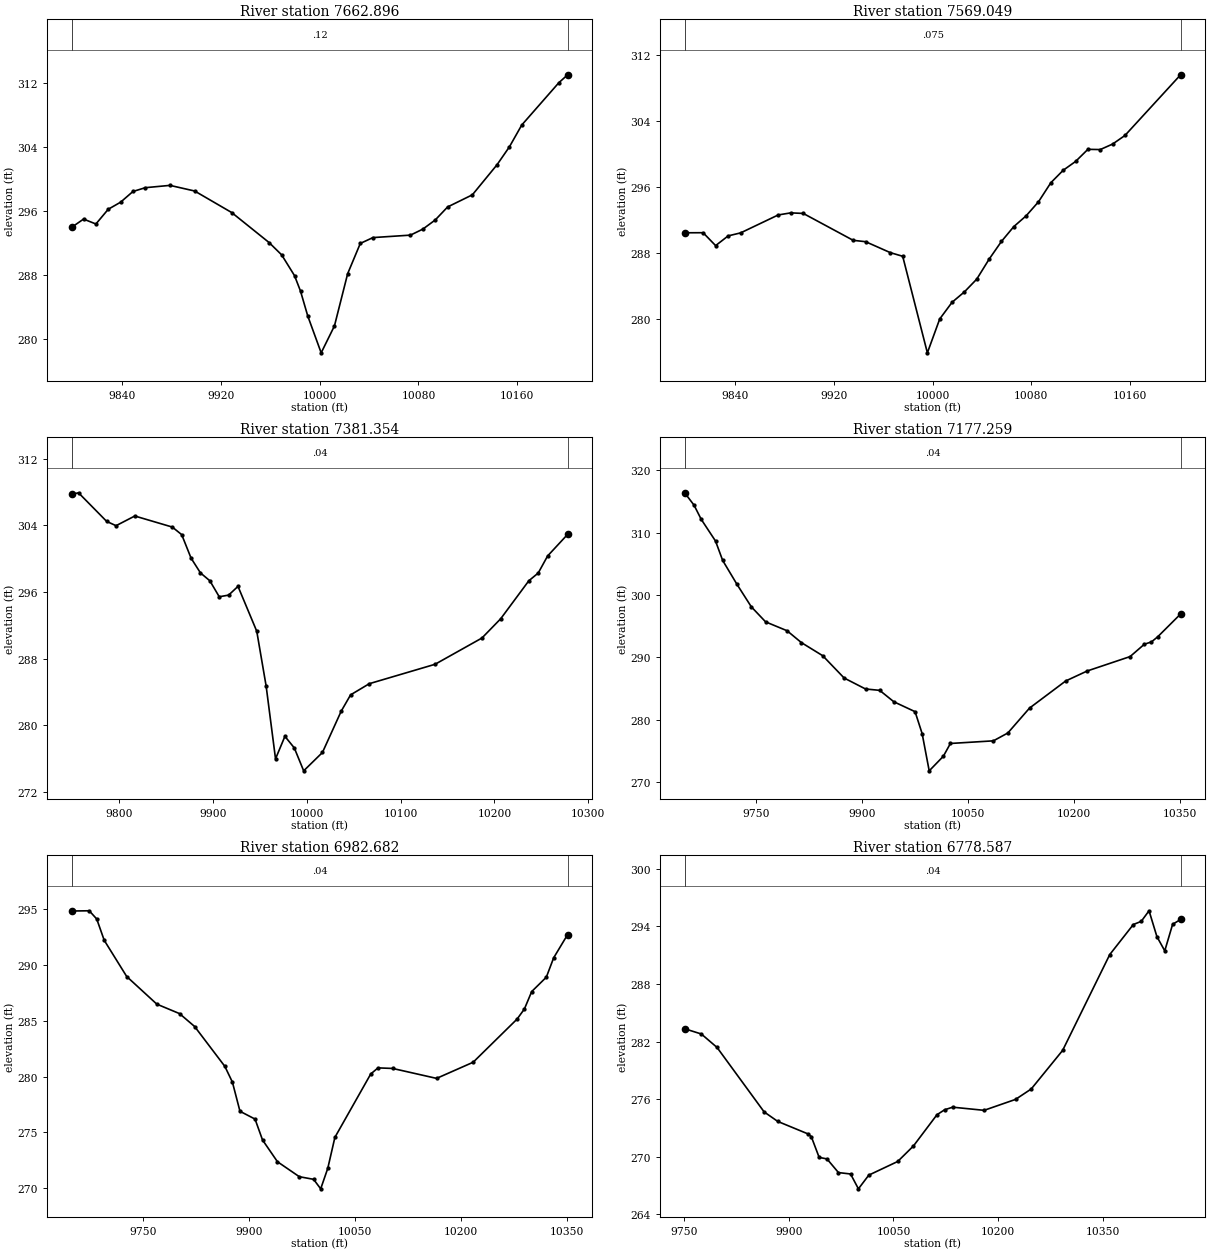
Type RM Length L Ch R = 1 ,7662.896,93.847300,93.847300,93.847300
XS GIS Cut Line= 6
464614.644879854747906.659410309464473.049956351747904.474075745
464439.996681493747898.653556036464395.909049169747881.152632946
464360.996441154747873.409289587464217.833992528 747867.56493798
#Sta/Elev= 30
9799.104293.91659808.749294.94639818.749294.33369828.749296.17659838.749 297.059
9848.749 298.397 9858.75298.8729 9878.75299.1625 9898.75 298.458 9928.78 295.763
9959.073292.00859969.227290.47189979.659287.87049984.496285.94189990.372282.8276
10001.24278.217610011.99281.5824 10022.7288.117210032.94291.902110043.18292.6324
10073.58292.939910083.62293.692710093.65294.836810103.69296.465110123.73297.9816
10143.73301.746510153.73303.982310163.73306.710110193.73311.9942 10200.9312.9953
#Mann= 3 , 0 , 0
9799.104    0.12       09799.104    0.12       0 10200.9    0.12       0
#XS Ineff= 2 , 0
       0                               0
Bank Sta=9799.104,10200.9
Exp/Cntr=0.3,0.1

Type RM Length L Ch R = 1 ,7569.049,187.694500,187.694500,187.694500
XS GIS Cut Line= 6
464619.754532347747820.838472234464500.471530559747800.473757744
464466.321806929747796.476953978464421.760484807747796.231367293
464349.604976233747797.963107309464219.935331898747792.043684443
#Sta/Elev= 30
9799.046290.41819814.014290.42759824.159288.86469834.304290.04219844.448290.4088
9874.882292.57739885.027292.82959895.172 292.7629935.632289.50599945.701289.3398
 9965.76 288.013 9975.76287.5742 9995.76275.884210005.76279.982310015.77282.0043
10025.77283.264110035.77284.807810045.77287.218310055.78289.371410065.78291.1649
10075.79292.4708 10085.8294.168710095.81296.476910105.82297.987110115.83299.0505
10125.84300.521510135.85300.493310145.86301.159410155.87302.199210200.98309.5475
#Mann= 3 , 0 , 0
9799.046   0.075       09799.046   0.075       010200.98   0.075       0
#XS Ineff= 2 , 0
       0                               0
Bank Sta=9799.046,10200.98
Exp/Cntr=0.3,0.1

Type RM Length L Ch R = 1 ,7381.354,204.095000,204.095000,204.095000
XS GIS Cut Line= 2
 464752.30005911747652.452783078464223.654225826747653.754866406
#Sta/Elev= 30
9749.487307.72389756.787307.90869786.787304.47569796.787303.95779816.787305.1208
9856.787303.79229866.787302.88229876.788300.05949886.788298.28919896.788297.3458
9906.788 295.4279916.788295.62539926.788296.67599946.788291.28519956.788284.7076
9966.788275.97349976.788278.67379986.788277.28519996.788274.533810016.79276.7372
10036.79281.694610046.79283.652410066.79284.996210136.79287.321810186.79290.4752
10206.79292.788610236.79297.349610246.79 298.27710256.79300.323910278.13302.9171
#Mann= 3 , 0 , 0
9749.487    0.04       09749.487    0.04       010278.13    0.04       0
#XS Ineff= 2 , 0
       0                               0
Bank Sta=9749.487,10278.13
Exp/Cntr=0.3,0.1

Type RM Length L Ch R = 1 ,7177.259,194.577500,194.577500,194.577500
XS GIS Cut Line= 6
464838.160704646747414.806369219 464585.65308422747452.463756144
464538.577556539747455.872895833464435.318872098 747457.00818353
464289.524850076747488.635785218464144.214188492 747509.62251207
#Sta/Elev= 30
9649.032316.38739662.358 314.3989672.483312.12829692.733308.64289702.859  305.53
9723.109301.6886 9743.36298.0917 9763.61295.67139793.986294.24539814.233292.3447
9844.492290.23239874.752286.65839905.007284.8989 9925.06284.67899945.112282.8451
9975.131281.25649985.132277.73839995.133271.761410015.14274.100410025.14276.1546
10085.94276.5753 10106.4277.8346 10137.1281.831510188.26286.181610218.77287.7892
 10279.4290.0985 10299.6292.078610309.71 292.45710318.58293.282910350.92296.9347
#Mann= 3 , 0 , 0
9649.032    0.04       09649.032    0.04       010350.92    0.04       0
#XS Ineff= 2 , 0
       0                               0
Bank Sta=9649.032,10350.92
Exp/Cntr=0.3,0.1

Type RM Length L Ch R = 1 ,6982.682,204.095000,204.095000,204.095000
XS GIS Cut Line= 6
464728.463277809747192.071718162464450.453191823747293.775131667
464420.223903403747300.802356304464363.264152916747306.594077874
464320.451306073747314.740989913464055.894351283747386.028546092
#Sta/Elev= 30
9649.043294.86429673.926294.88479684.531294.14819695.136292.2326 9726.95288.9816
9769.602286.49849801.688285.65019823.079284.49089865.861280.90989876.557279.4928
9887.252276.87699908.575276.17719919.147274.30379940.291272.3468 9971.23 271.002
9991.443270.765710001.49269.911610011.54271.760610021.59274.535810072.34280.2293
10082.61280.774810103.33280.724610165.47279.831610217.25281.281610279.39285.1564
10289.75286.059810300.11287.629210320.82288.921410331.18290.658910350.96292.7509
#Mann= 3 , 0 , 0
9649.043    0.04       09649.043    0.04       010350.96    0.04       0
#XS Ineff= 2 , 0
       0                               0
Bank Sta=9649.043,10350.96
Exp/Cntr=0.3,0.1

Type RM Length L Ch R = 1 ,6778.587,87.559300,87.559300,87.559300
XS GIS Cut Line= 2
464576.231805205 747013.58461608463944.818518013747340.574545249
#Sta/Elev= 30
9750.618283.33449774.528282.78759797.051281.38769864.619274.6676 9884.17273.6774
9927.661272.37389932.188272.09739943.449269.9344 9954.71269.77149971.152268.3503
9988.495268.20489999.756266.656710014.64268.085310056.06269.505410078.59271.1176
10112.37274.376710123.37274.893910134.89275.162910179.94274.835410224.98275.9726
10247.51277.059210292.55281.079410360.12291.0635 10393.9294.190310405.17294.5166
10416.43 295.62210427.69 292.92910438.95291.449910450.21294.213710461.68294.7185
#Mann= 3 , 0 , 0
9750.618    0.04       09750.618    0.04       010461.68    0.04       0
#XS Ineff= 2 , 0
       09890.453                       0
Bank Sta=9750.618,10461.68
Exp/Cntr=0.3,0.1

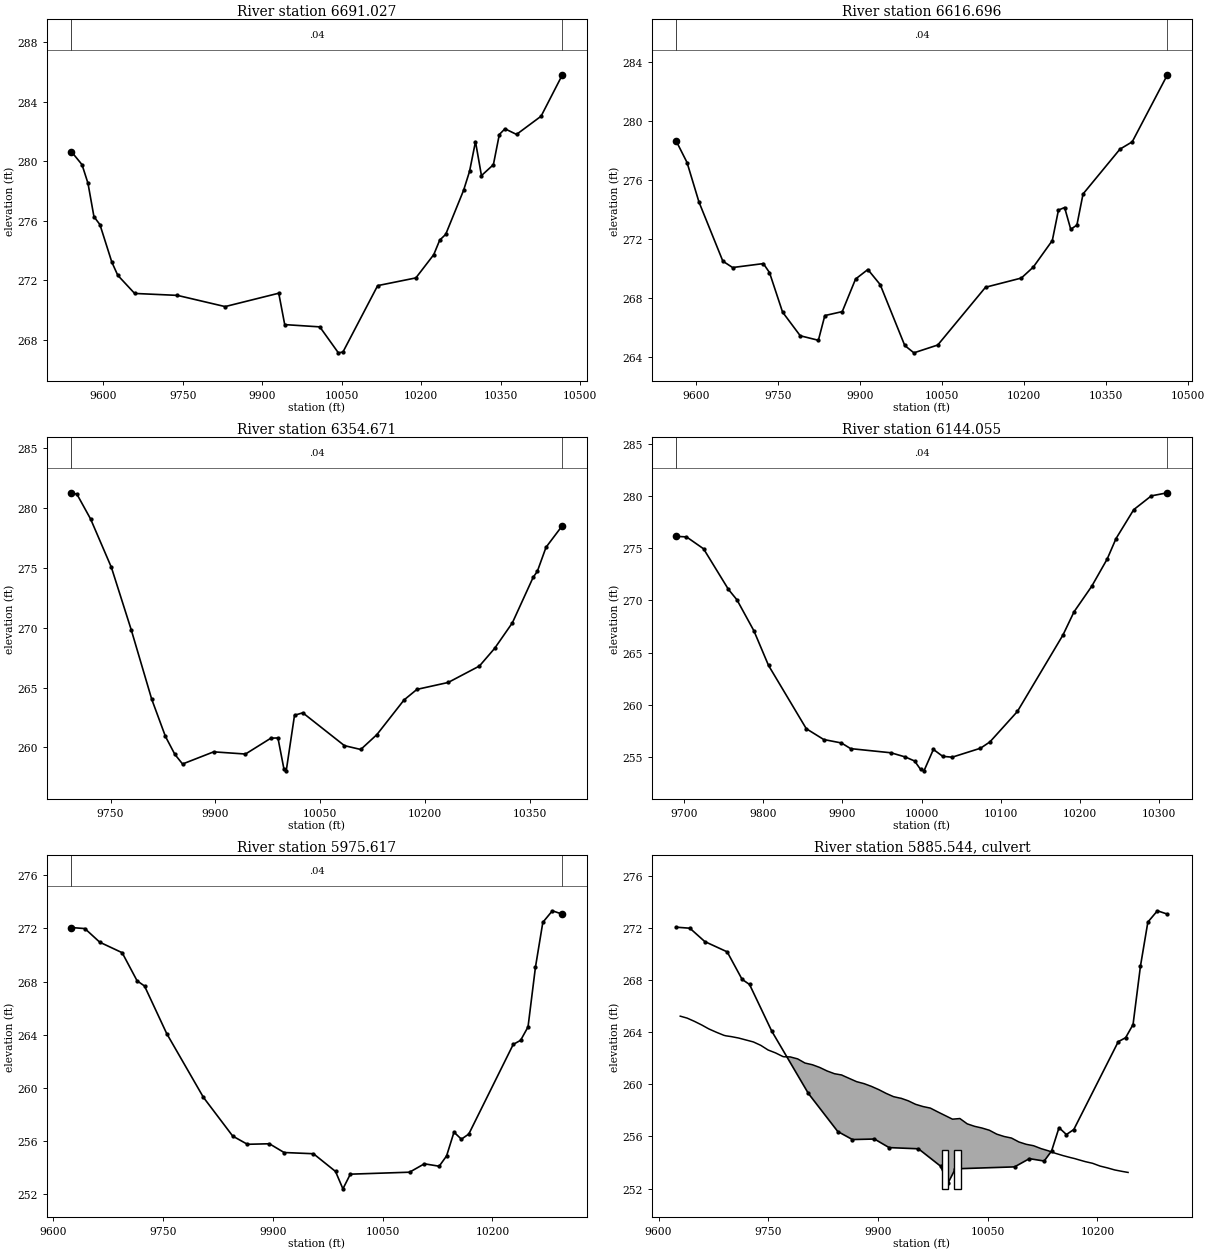
Type RM Length L Ch R = 1 ,6691.027,74.331100,74.331100,74.331100
XS GIS Cut Line= 2
464722.813309669746840.357531354463899.245601356 747264.61968416
#Sta/Elev= 30
9539.761280.65049559.799279.77719571.048 278.5269582.297276.28489593.571275.7521
9616.044273.23039627.292 272.3449659.079271.12789739.782270.99729829.773270.2446
9931.013271.14319942.262269.034410008.46268.8819 10043.5 267.13810052.13267.1926
10117.64271.652610189.74272.171210223.49273.734110234.73274.709810245.98275.0936
10279.73278.051110290.98279.322810302.23281.325710313.48279.0424   10336279.7763
10347.22281.803110357.84282.186510379.67281.808710425.97283.031110466.19285.8146
#Mann= 3 , 0 , 0
9539.761    0.04       09539.761    0.04       010466.19    0.04       0
#XS Ineff= 2 , 0
       09903.183        10115.95       0
Bank Sta=9539.761,10466.19
Exp/Cntr=0.3,0.1

Type RM Length L Ch R = 1 ,6616.696,262.024900,262.024900,262.024900
XS GIS Cut Line= 2
464666.389698565746786.104059145463867.778587461747197.345378578
#Sta/Elev= 30
9563.646278.62839583.077277.2009 9604.92274.51679648.606 270.504 9666.44270.0724
 9722.68270.33979733.928269.73079757.821267.04879790.168265.4404 9823.35265.1336
 9835.16266.81229867.036267.0799  9891.4269.29269913.896269.93869936.392268.9164
9981.384264.78079998.095264.281510041.78264.813310129.15268.733510194.68269.3586
10216.52270.101410251.34 271.90510262.58273.971410273.83274.147310285.08272.6663
10296.33 272.95510307.57275.066210375.06278.107310397.56278.606610461.92283.1574
#Mann= 3 , 0 , 0
9563.646    0.04       09563.646    0.04       010461.92    0.04       0
#XS Ineff= 2 , 0
       09913.617        10103.72       0
Bank Sta=9563.646,10461.92
Exp/Cntr=0.3,0.1

Type RM Length L Ch R = 1 ,6354.671,210.616300,210.616300,210.616300
XS GIS Cut Line= 6
464412.440045834746635.748156354464321.905877858746668.788687959
 464236.79417491746708.564707816463983.438920707746859.501460657
463888.100623995746907.360787094463794.861920804 746967.74468413
#Sta/Elev= 30
9693.886 281.2589701.787281.14069721.394279.06669751.126275.03379779.622269.8081
9808.927264.02019828.556 260.9169842.041259.41999853.079258.61529897.641259.6301
 9943.18259.44659979.671260.77459989.668260.78979998.244 258.20210001.54258.0441
 10013.4262.683210025.27262.888910084.87260.148910108.25259.826810131.32261.0649
10170.25263.960410188.72264.844410233.47265.421710278.23266.7948   10300268.2684
10325.39270.398710355.19274.202110361.13274.693610373.59276.706410397.03278.5211
#Mann= 3 , 0 , 0
9693.886    0.04       09693.886    0.04       010397.03    0.04       0
#XS Ineff= 2 , 0
       09891.075        10046.85       0
Bank Sta=9693.886,10397.03
Exp/Cntr=0.3,0.1

Type RM Length L Ch R = 1 ,6144.055,168.438200,168.438200,168.438200
XS GIS Cut Line= 6
464306.971295804746453.456489682464216.437127858746486.497021288
 464131.32542491746526.273041144464059.222506374746565.509504259
463877.970170707 746677.20979397463756.393167138746736.795656055
#Sta/Elev= 30
9690.104276.12129702.815276.07449724.425274.93349755.918271.04039766.619 270.049
9788.069267.08019806.566263.76239854.298257.70499876.375256.66899898.688256.3393
9910.401255.79699961.452255.39879979.396255.00049991.263254.61189998.718253.8151
10003.13253.6702   10015255.720110026.86255.057810038.78254.977910074.57255.8363
 10086.5256.440910121.23259.355110178.81266.671610192.86268.900310215.14271.3362
10234.76273.952510245.95275.914210268.33278.682210290.53280.001410310.91280.2981
#Mann= 3 , 0 , 0
9690.104    0.04       09690.104    0.04       010310.91    0.04       0
#XS Ineff= 2 , 0
       09889.366        10053.59       0
Bank Sta=9690.104,10310.91
Exp/Cntr=0.3,0.1

Type RM Length L Ch R = 1 ,5975.617,177.626300,177.626300,177.626300
XS GIS Cut Line= 5
464313.047684669 746397.90093413464203.672684669746419.602323025
463963.262806207 746438.09803021463895.177983314746448.701404288
463648.596442461746487.103447512
#Sta/Elev= 30
9624.497272.07059642.896271.99299663.286270.96689693.871270.17819714.261268.0658
9724.456267.67149754.732264.09599804.879259.30179844.998256.38239865.057255.7651
9895.145255.80449915.204255.14679955.323255.05469985.486253.72299995.607252.4137
10005.73 253.51710086.69253.665610106.93254.297510127.17 254.11510137.29254.8891
10147.42256.677110157.54256.149710167.66256.536510228.38263.2783 10238.5263.5885
10248.62264.595910258.74269.081410268.86272.463910281.91 273.33210295.58273.0742
#Mann= 3 , 0 , 0
9624.497    0.04       09624.497    0.04       010295.58    0.04       0
#XS Ineff= 2 , 0
       09954.007        10035.61       0
Bank Sta=9624.497,10295.58
Exp/Cntr=0.3,0.1

Type RM Length L Ch R = 2 ,5885.544,,,
Bridge Culvert--1,0,-1,-1, 0
Deck Dist Width WeirC Skew NumUp NumDn MinLoCord MaxHiCord MaxSubmerge Is_Ogee
38.378,100.87,2.6,0,70,70, , , 0.95, 0, 0,0,,
 9629.71 9639.12 9649.14 9659.16 9667.81 9669.19 9679.27 9689.35 9692.18 9699.43
 9709.51 9719.59 9729.67 9739.75 9749.83 9759.91 9769.99 9771.65 9780.07 9790.15
 9800.23 9810.32 9820.40 9830.48 9840.56 9850.64 9851.13 9860.72 9870.80 9880.88
 9890.96 9901.04 9911.12 9921.20 9930.61 9931.28 9941.36 9951.44 9961.52 9971.60
 9981.68 9991.7610001.8410010.0910011.9210022.0010032.0810042.1610052.2410062.32
10072.4010082.4810089.5710092.5610102.6410112.7210122.8010132.8810142.9610153.04
10163.1210169.0410173.2010183.2810193.3610203.4410213.5210223.6010233.6810241.82
  265.24  265.09  264.84  264.56  264.29  264.25  264.00  263.77  263.73  263.67
  263.56  263.41  263.26  263.00  262.64  262.42  262.14  262.12  262.11  261.96
  261.64  261.51  261.30  261.03  260.82  260.72  260.70  260.46  260.21  260.06
  259.85  259.60  259.31  259.06  258.94  258.94  258.74  258.47  258.30  258.18
  257.89  257.61  257.33  257.37  257.38  256.97  256.78  256.65  256.48  256.18
  256.00  255.88  255.67  255.58  255.40  255.29  255.07  254.90  254.70  254.53
  254.38  254.30  254.23  254.07  253.94  253.73  253.59  253.43  253.32  253.24
                                                                                
                                                                                
                                                                                
                                                                                
                                                                                
                                                                                
                                                                                
 9629.71 9639.12 9649.14 9659.16 9667.81 9669.19 9679.27 9689.35 9692.18 9699.43
 9709.51 9719.59 9729.67 9739.75 9749.83 9759.91 9769.99 9771.65 9780.07 9790.15
 9800.23 9810.32 9820.40 9830.48 9840.56 9850.64 9851.13 9860.72 9870.80 9880.88
 9890.96 9901.04 9911.12 9921.20 9930.61 9931.28 9941.36 9951.44 9961.52 9971.60
 9981.68 9991.7610001.8410010.0910011.9210022.0010032.0810042.1610052.2410062.32
10072.4010082.4810089.5710092.5610102.6410112.7210122.8010132.8810142.9610153.04
10163.1210169.0410173.2010183.2810193.3610203.4410213.5210223.6010233.6810241.82
  265.24  265.09  264.84  264.56  264.29  264.25  264.00  263.77  263.73  263.67
  263.56  263.41  263.26  263.00  262.64  262.42  262.14  262.12  262.11  261.96
  261.64  261.51  261.30  261.03  260.82  260.72  260.70  260.46  260.21  260.06
  259.85  259.60  259.31  259.06  258.94  258.94  258.74  258.47  258.30  258.18
  257.89  257.61  257.33  257.37  257.38  256.97  256.78  256.65  256.48  256.18
  256.00  255.88  255.67  255.58  255.40  255.29  255.07  254.90  254.70  254.53
  254.38  254.30  254.23  254.07  253.94  253.73  253.59  253.43  253.32  253.24
                                                                                
                                                                                
                                                                                
                                                                                
                                                                                
                                                                                
                                                                                
BR Coef=-1 , 0 , 0 ,, 0 ,,,0.8,-1,,0,
WSPro=,,,, 1 ,,,, 0 ,,,, 0 ,,,,-1 ,-1 ,-1 , 0 , 0 , 0 , 0 , 0
Multiple Barrel Culv=2,3,8.75,100.87,0.013,0.4,1,8,1,251.98,247.54,2,Culvert #1, 0, 38.378
 9991.25 9991.2510008.7510008.75
Culvert Bottom n=0.013
BC Design=,, 0 ,, 0 ,,,,,,

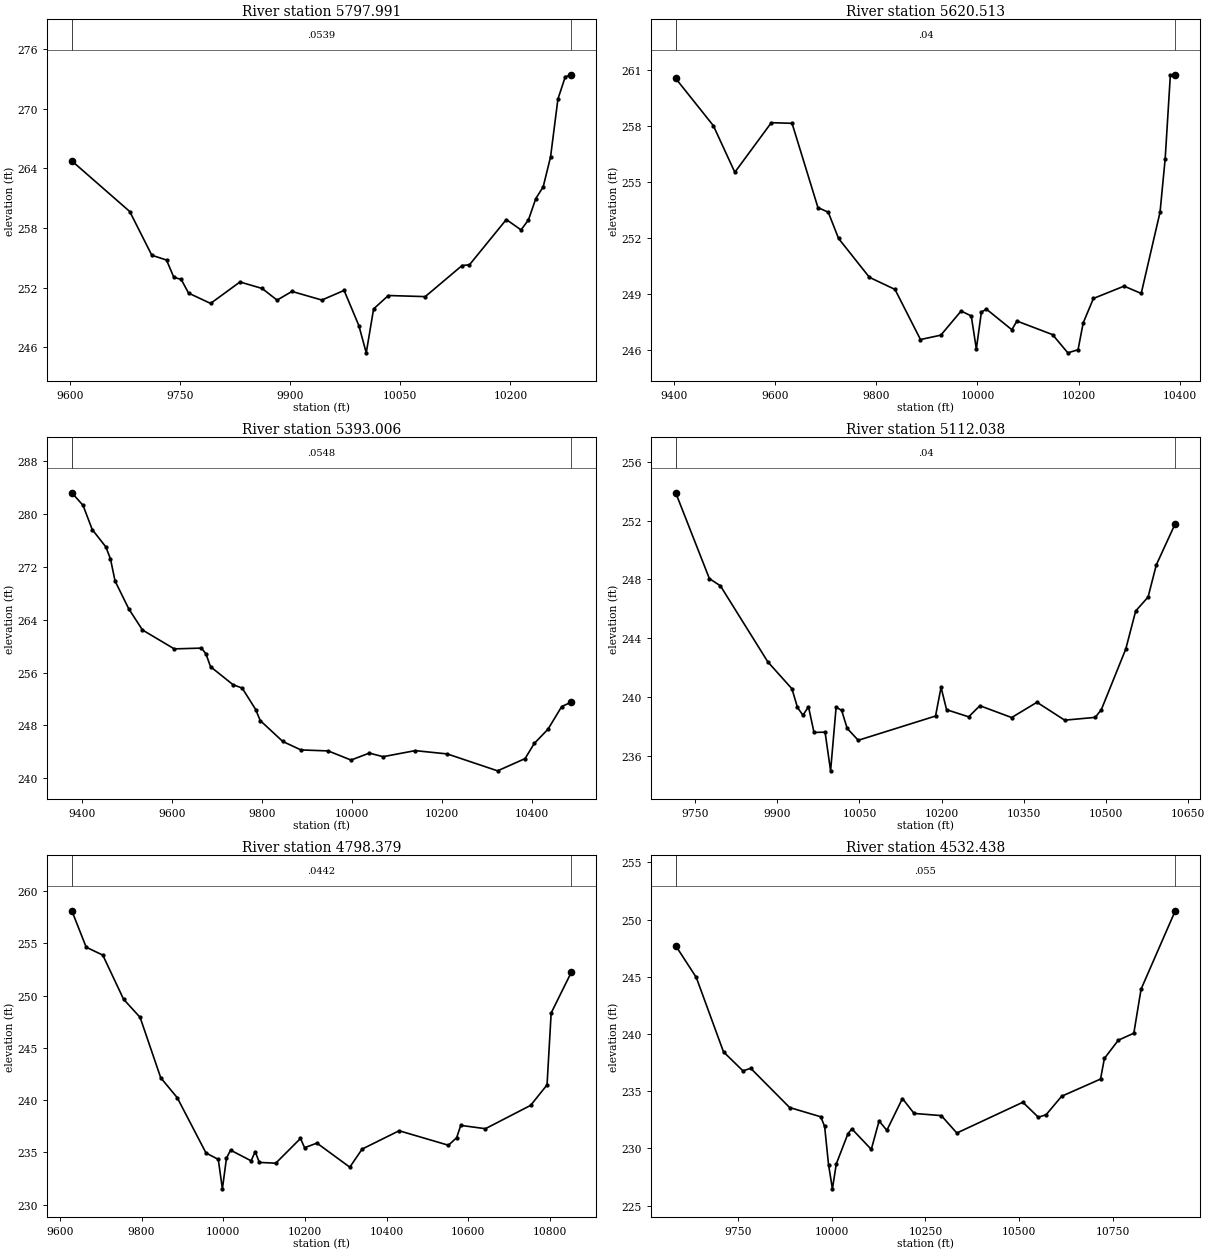
Type RM Length L Ch R = 1 ,5797.991,177.477500,177.477500,177.477500
XS GIS Cut Line= 4
464313.827633023746255.735362723464063.853346676746243.172345042
463956.190045804746263.005100802463636.745601356746293.387045234
#Sta/Elev= 30
9602.419264.73469681.346259.64899711.384255.25659731.409254.77479741.422253.0383
9751.434252.82829761.447251.45099791.485 250.4149831.535252.56969861.711251.9181
9882.047250.74679902.384 251.6199943.057250.75439973.424251.71989993.514248.1808
10003.56245.4479 10013.6249.863110033.69251.209610083.92251.097810134.15254.2229
10144.19254.294810194.42258.845110214.51257.802510224.55258.8038 10234.6260.9547
10244.64262.126410254.69265.138110264.73270.956610274.78273.194310283.07273.3932
#Mann= 3 , 0 , 0
9602.419  0.0539       09602.419  0.0539       010283.07  0.0539       0
#XS Ineff= 2 , 0
       09950.898         10051.2       0
Bank Sta=9602.419,10283.07
Exp/Cntr=0.3,0.1

Type RM Length L Ch R = 1 ,5620.513,227.507000,227.507000,227.507000
XS GIS Cut Line= 6
464507.989265919745985.795607507464317.855180353746033.852500051
 464147.62319243746067.345511228464010.412570208746084.749872088
463753.061104029746103.219660372463535.420473266746136.670816696
#Sta/Elev= 30
9404.235260.53599478.613258.00489520.954255.51099593.007 258.1679633.939 258.133
9685.038253.6215 9705.44253.37269725.755251.96689786.632249.88579837.153249.2373
 9887.48 246.553 9927.65246.7877 9967.72248.07929987.755247.81679997.772246.0485
10007.78248.0257 10017.8248.178710067.87247.078710077.91247.543310148.24246.8167
10178.41245.8409 10198.6246.0058 10208.7247.439310228.89248.752610289.45249.4133
 10323.3 249.02210360.47253.375710370.63256.247110380.78260.696710390.51260.7329
#Mann= 3 , 0 , 0
9404.235    0.04       09404.235    0.04       010390.51    0.04       0
#XS Ineff= 2 , 0
       09973.028         10094.2       0
Bank Sta=9404.235,10390.51
Exp/Cntr=0.3,0.1

Type RM Length L Ch R = 1 ,5393.006,280.968400,280.968400,280.968400
XS GIS Cut Line= 6
464489.355329186745783.376071706464346.172654808745810.417036384
464252.741639614745823.860103324464026.422358871 745846.76780054
463917.376545995745860.825072929463393.907059669745961.572809115
#Sta/Elev= 30
9377.337 283.1749402.263281.27269422.661277.61659453.141274.97679463.301273.1553
9473.461269.8348 9503.94265.62599534.356262.43629605.077259.57819665.515259.6943
 9675.58258.81479685.645256.89069735.898254.15559755.982253.6598  9786.1250.4099
9796.147248.74299846.388245.57949886.719244.30189947.215244.15389998.056242.7731
10038.79243.823410069.34243.281510140.63244.195610211.91243.700310323.93241.1421
10385.03242.9928 10405.4245.278810435.95247.4324 10466.5250.864910487.98251.5305
#Mann= 3 , 0 , 0
9377.337  0.0548       09377.337  0.0548       010487.98  0.0548       0
#XS Ineff= 2 , 0
       09963.048        10095.43       0
Bank Sta=9377.337,10487.98
Exp/Cntr=0.3,0.1

Type RM Length L Ch R = 1 ,5112.038,313.658600,313.658600,313.658600
XS GIS Cut Line= 6
464116.022889763745563.443436638 463889.70360893745586.351133868
463568.404242575745626.898378283463529.150115371745644.009151727
463498.768170804745665.710540622463373.073726356745915.999892458
#Sta/Elev= 30
9714.756253.89669776.177248.06079796.308247.5671 9882.92242.3898 9926.88 240.563
9936.927239.29559946.991238.76469957.073239.34129967.156237.59159987.322237.6135
9997.404234.980810007.49239.312410017.57239.093610027.65237.871710047.82237.0597
10188.91238.708510198.98240.661610209.06239.139810249.37238.654510269.81239.4111
10327.83 238.606   10374239.645210424.62238.427210480.36238.6182 10491.5 239.145
 10536.1 243.26910554.15245.853510576.77246.802710591.83248.992710626.39251.8014
#Mann= 3 , 0 , 0
9714.756    0.04       09714.756    0.04       010626.39    0.04       0
#XS Ineff= 2 , 0
       0                10118.83       0
Bank Sta=9714.756,10626.39
Exp/Cntr=0.3,0.1

Type RM Length L Ch R = 1 ,4798.379,265.941100,265.941100,265.941100
XS GIS Cut Line= 6
464169.348042101745228.564634249464026.165367723745255.605598956
463932.734352559745269.048665881463706.415071815745291.956363112
 463597.36925894745306.013635471462955.776272684745376.616211891
#Sta/Elev= 30
9629.208258.12829664.362254.64329705.005253.88559755.805249.66929796.324247.9276
9846.839242.14649887.184240.24559957.638234.95099987.763234.33269997.804231.5152
10007.85234.459610017.89235.219410068.11234.196110078.15235.0772 10088.2234.0449
 10128.5233.9705   10189 236.33810199.08 235.45110229.28235.892310309.76233.5891
10339.94235.321410430.49237.074310551.21235.687610571.33236.409910581.39237.5889
10641.75 237.27110752.42239.503210792.66241.462710802.72 248.34310852.24252.2573
#Mann= 3 , 0 , 0
9629.208  0.0442       09629.208  0.0442       010852.24  0.0442       0
#XS Ineff= 2 , 0
       0                10150.37       0
Bank Sta=9629.208,10852.24
Exp/Cntr=0.3,0.1

Type RM Length L Ch R = 1 ,4532.438,71.030500,71.030500,71.030500
XS GIS Cut Line= 4
464167.914582819744922.527670234463467.683101416745110.788665593
463029.128414184 745225.91349113 462940.51296249745348.896304488
#Sta/Elev= 30
9585.144247.71289639.938244.94219712.424238.43739764.199236.7817 9784.91237.0021
9888.461233.57779971.302232.76879981.657231.92689992.012228.600510002.37226.4743
10012.72228.653710043.79231.295610054.14231.713510105.92229.920310126.63232.4041
10147.34231.587110188.76234.364310219.82233.062210292.31232.871810333.69231.3497
10509.45234.039310550.81232.726210571.49 232.95410612.84234.565110716.23236.0629
10726.57237.869310763.66239.459310804.93 240.07210824.16243.912810915.24250.7655
#Mann= 3 , 0 , 0
9585.144   0.055       09585.144   0.055       010915.24   0.055       0
#XS Ineff= 2 , 0
       09960.807        10053.61       0
Bank Sta=9585.144,10915.24
Exp/Cntr=0.3,0.1