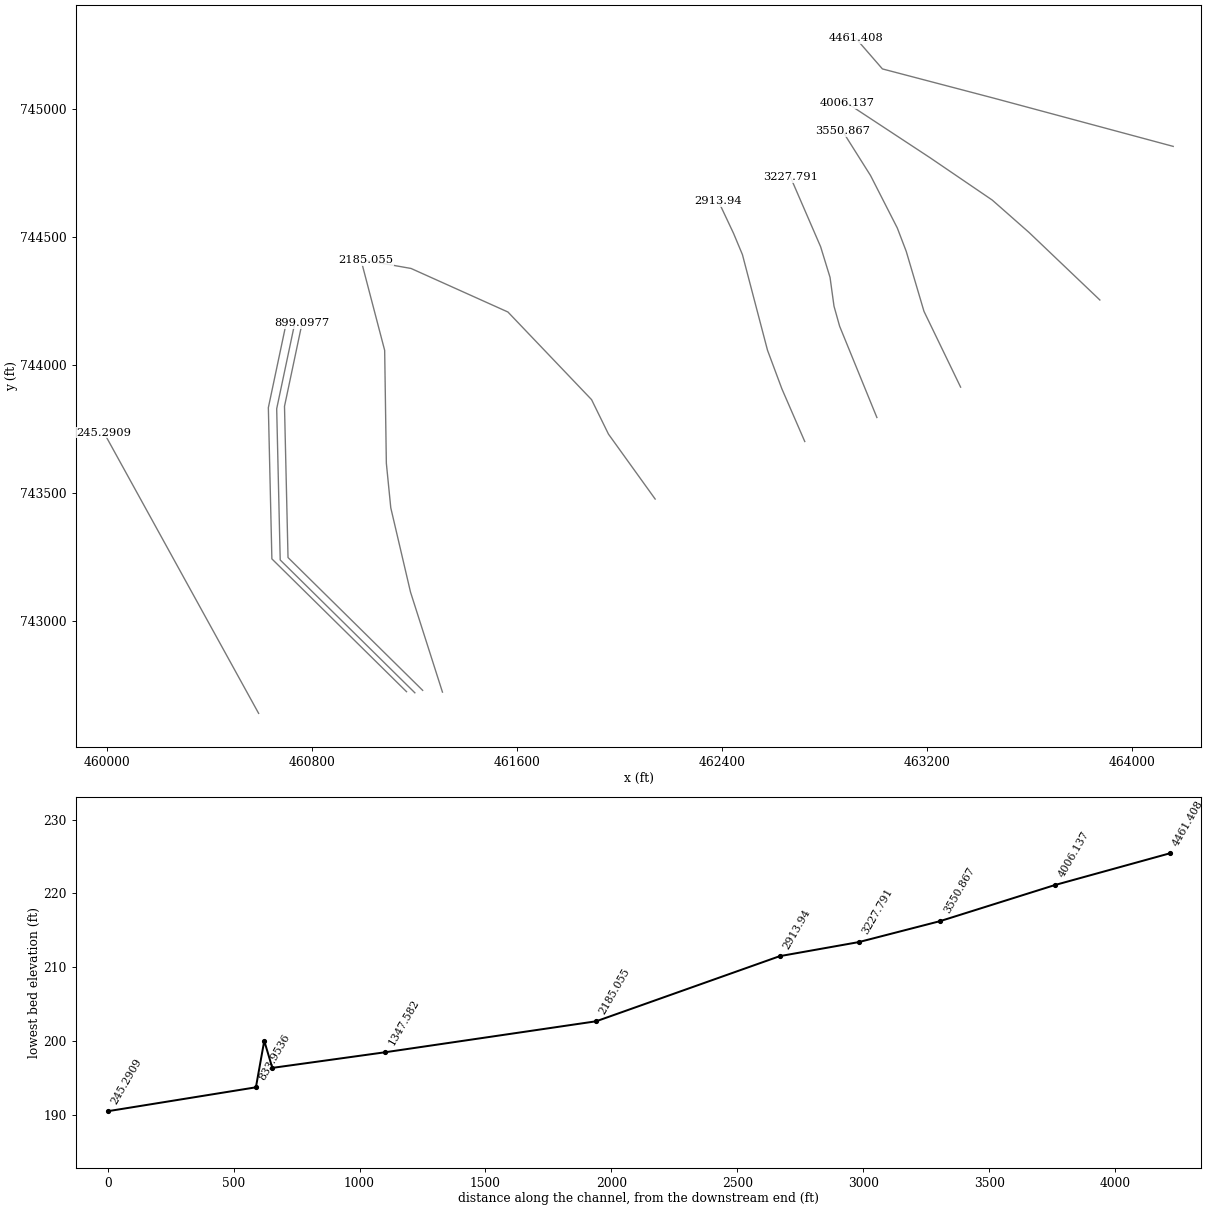
HEC-RAS study 2598_ras.prj: 2598

--- 2598_ras.g01 (geometry) --- (continued)

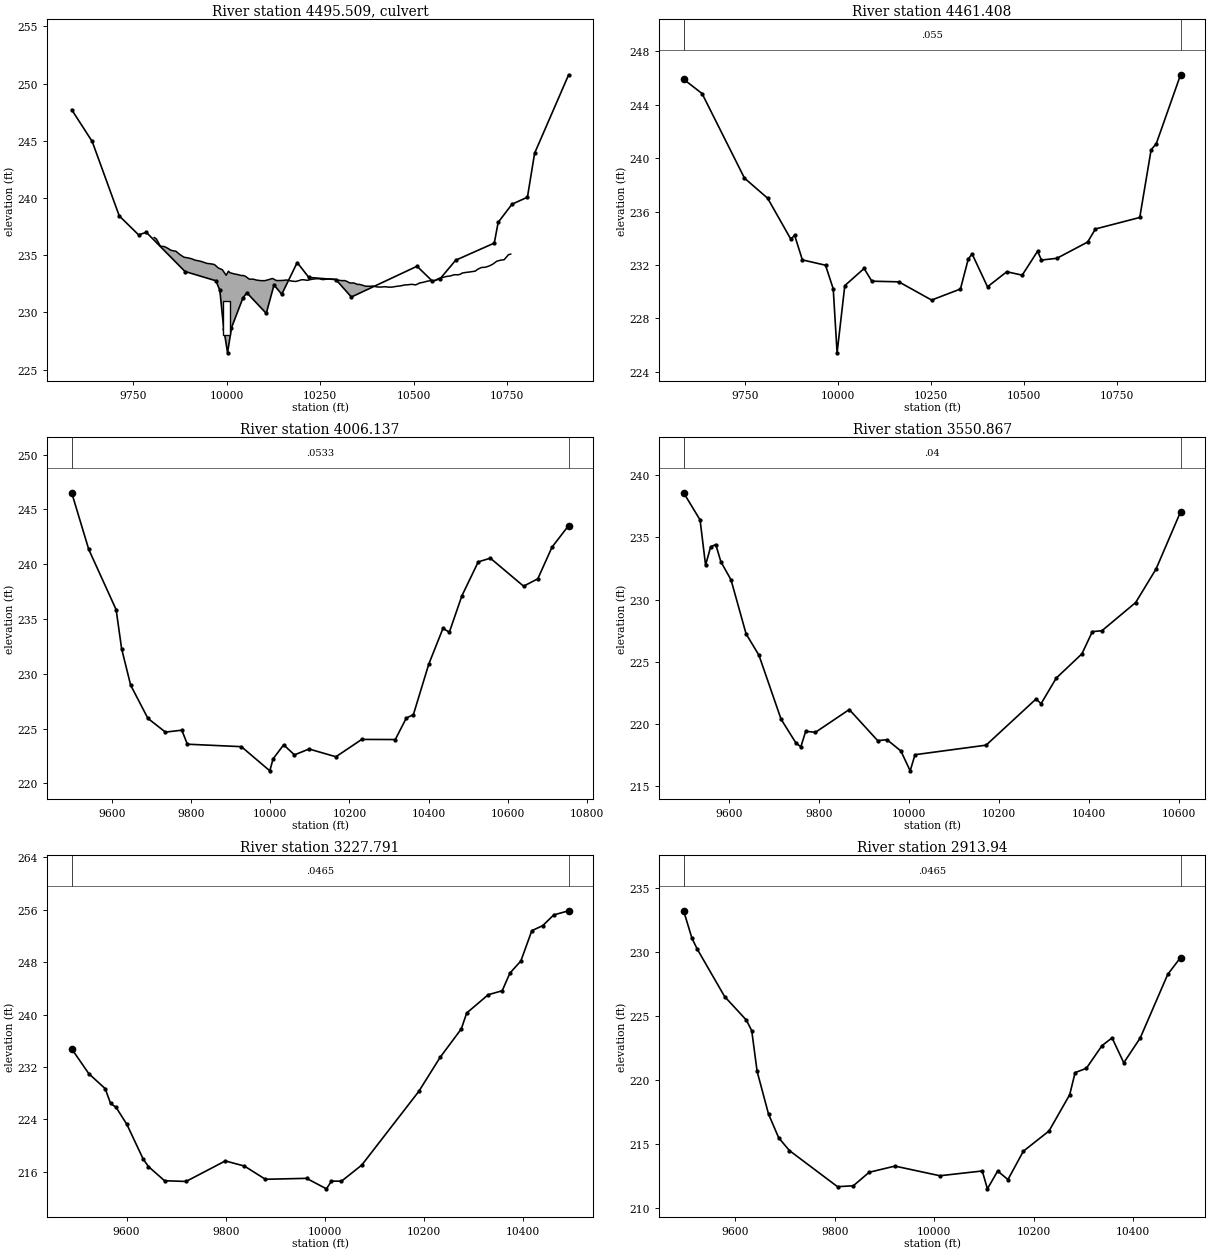
Type RM Length L Ch R = 2 ,4495.509,,,
Bridge Culvert--1,0,-1,-1, 0
Deck Dist Width WeirC Skew NumUp NumDn MinLoCord MaxHiCord MaxSubmerge Is_Ogee
24.515,22,2.6,0,119,119, , , 0.95, 0, 0,0,,
 9805.91 9810.50 9812.27 9822.62 9832.97 9843.32 9849.34 9853.67 9864.02 9874.36
 9884.71 9888.19 9895.06 9905.41 9915.76 9926.11 9927.03 9936.46 9946.81 9957.15
 9965.88 9967.50 9977.85 9988.20 9998.5510004.7210008.9010019.2510029.6010039.94
10043.5710050.2910060.6410070.9910081.3410082.4110091.6910102.0410112.3910121.26
10122.7410133.0810143.4310153.7810160.1010164.1310174.4810184.8310195.1810198.95
10205.5310215.8710226.2210236.5710237.8010246.9210257.2710267.6210276.6410277.97
10288.3210298.6610309.0110315.4910319.3610329.7110340.0610350.4110354.3310360.76
10371.1110381.4510391.8010393.1810402.1510412.5010422.8510432.0210433.2010443.55
10453.9010464.2510470.8710474.5910484.9410495.2910505.6410509.7110515.9910526.34
10536.6910547.0410548.5610557.3810567.7310578.0810587.4010588.4310598.7810609.13
10619.4810626.2510629.8310640.1710650.5210660.8710665.0910671.2210681.5710691.92
10702.2710703.9410712.6210722.9710733.3110742.7810743.6610754.0110760.09
  236.55  236.46  236.40  235.79  235.76  235.59  235.46  235.41  235.35  235.07
  234.85  234.81  234.78  234.70  234.57  234.50  234.50  234.41  234.29  234.25
  234.20  234.18  233.88  233.74  233.25  233.61  233.47  233.38  233.31  233.22
  233.24  233.16  232.91  232.91  232.82  232.82  232.78  232.78  232.87  232.96
  232.97  232.79  232.79  232.81  232.84  232.81  232.74  232.71  232.80  232.85
  232.86  232.81  232.89  232.94  232.94  232.95  232.87  232.91  232.93  232.93
  232.90  232.82  232.78  232.79  232.75  232.58  232.58  232.45  232.46  232.41
  232.30  232.29  232.31  232.30  232.23  232.22  232.25  232.22  232.21  232.22
  232.28  232.32  232.36  232.40  232.42  232.46  232.41  232.47  232.57  232.64
  232.73  232.79  232.78  232.79  232.97  233.06  233.14  233.15  233.19  233.30
  233.29  233.35  233.44  233.50  233.54  233.59  233.61  233.76  233.93  233.95
  234.06  234.08  234.23  234.48  234.57  234.61  234.65  235.04  235.10
                                                                                
                                                                                
                                                                                
                                                                                
                                                                                
                                                                                
                                                                                
                                                                                
                                                                                
                                                                                
                                                                                
                                                                        
 9805.91 9810.50 9812.27 9822.62 9832.97 9843.32 9849.34 9853.67 9864.02 9874.36
 9884.71 9888.19 9895.06 9905.41 9915.76 9926.11 9927.03 9936.46 9946.81 9957.15
 9965.88 9967.50 9977.85 9988.20 9998.5510004.7210008.9010019.2510029.6010039.94
10043.5710050.2910060.6410070.9910081.3410082.4110091.6910102.0410112.3910121.26
10122.7410133.0810143.4310153.7810160.1010164.1310174.4810184.8310195.1810198.95
10205.5310215.8710226.2210236.5710237.8010246.9210257.2710267.6210276.6410277.97
10288.3210298.6610309.0110315.4910319.3610329.7110340.0610350.4110354.3310360.76
10371.1110381.4510391.8010393.1810402.1510412.5010422.8510432.0210433.2010443.55
10453.9010464.2510470.8710474.5910484.9410495.2910505.6410509.7110515.9910526.34
10536.6910547.0410548.5610557.3810567.7310578.0810587.4010588.4310598.7810609.13
10619.4810626.2510629.8310640.1710650.5210660.8710665.0910671.2210681.5710691.92
10702.2710703.9410712.6210722.9710733.3110742.7810743.6610754.0110760.09
  236.55  236.46  236.40  235.79  235.76  235.59  235.46  235.41  235.35  235.07
  234.85  234.81  234.78  234.70  234.57  234.50  234.50  234.41  234.29  234.25
  234.20  234.18  233.88  233.74  233.25  233.61  233.47  233.38  233.31  233.22
  233.24  233.16  232.91  232.91  232.82  232.82  232.78  232.78  232.87  232.96
  232.97  232.79  232.79  232.81  232.84  232.81  232.74  232.71  232.80  232.85
  232.86  232.81  232.89  232.94  232.94  232.95  232.87  232.91  232.93  232.93
  232.90  232.82  232.78  232.79  232.75  232.58  232.58  232.45  232.46  232.41
  232.30  232.29  232.31  232.30  232.23  232.22  232.25  232.22  232.21  232.22
  232.28  232.32  232.36  232.40  232.42  232.46  232.41  232.47  232.57  232.64
  232.73  232.79  232.78  232.79  232.97  233.06  233.14  233.15  233.19  233.30
  233.29  233.35  233.44  233.50  233.54  233.59  233.61  233.76  233.93  233.95
  234.06  234.08  234.23  234.48  234.57  234.61  234.65  235.04  235.10
                                                                                
                                                                                
                                                                                
                                                                                
                                                                                
                                                                                
                                                                                
                                                                                
                                                                                
                                                                                
                                                                                
                                                                        
BR Coef=-1 , 0 , 0 ,, 0 ,,,0.8,-1,,0,
WSPro=,,,, 1 ,,,, 0 ,,,, 0 ,,,,-1 ,-1 ,-1 , 0 , 0 , 0 , 0 , 0
Culvert=2,3,20,22,0.013,0.5,1,8,3,228,10000,226,10000,Culvert #1, 0, 24.515
Culvert Bottom n=0.013
BC Design=,, 0 ,, 0 ,,,,,,

Type RM Length L Ch R = 1 ,4461.408,455.270500,455.270500,455.270500
XS GIS Cut Line= 4
464162.706249475744852.215170234463462.474768043745040.476165593
463026.955271214745154.804224446462923.151851356745274.243526712
#Sta/Elev= 30
9586.051245.91249635.451 244.8449749.358238.50669811.488237.00439873.619233.9428
9883.974 234.2269904.684232.38579966.815231.98589987.525230.2174 9997.88225.4245
10018.59 230.45710070.37231.743310091.08230.790310163.56230.741810251.54229.3762
10328.97230.206310349.89232.448810360.23232.830210401.59230.369110453.28231.4984
10494.64231.241210535.99233.035410546.33232.374110587.69232.5034 10670.4233.7233
10691.07234.699310810.14235.561810840.63240.629610854.43241.087210919.67246.2481
#Mann= 3 , 0 , 0
9586.051   0.055       09586.051   0.055       010919.67   0.055       0
#XS Ineff= 2 , 0
       09969.212        10046.57       0
Bank Sta=9586.051,10919.67
Exp/Cntr=0.3,0.1

Type RM Length L Ch R = 1 ,4006.137,455.270400,455.270400,455.270400
XS GIS Cut Line= 6
463876.177141815744252.319805935463599.956126004744515.693063393
463509.689786047744595.250483587463455.770613611744642.636533991
463213.320024401744807.711752981462889.969329953745020.385364085
#Sta/Elev= 30
9499.019246.52129542.097241.34389611.183235.8486    9625232.28479647.815228.9544
9691.288225.92969735.537224.67169776.989224.84949790.806223.56939927.266223.3437
    9999221.137410007.24222.232910033.87223.510610061.21222.594410097.91223.1309
10165.82222.422610230.99 224.00610315.67223.994810343.51225.960410361.28226.2661
10399.99230.8632 10435.9 234.13310452.15233.805110483.77237.117810524.94240.2121
10555.59 240.55110639.37237.996710675.28238.666410711.19241.560710753.12243.5267
#Mann= 3 , 0 , 0
9499.019  0.0533       09499.019  0.0533       010753.12  0.0533       0
#XS Ineff= 2 , 0
       09933.426        10135.95       0
Bank Sta=9499.019,10753.12
Exp/Cntr=0.3,0.1

Type RM Length L Ch R = 1 ,3550.867,323.075700,323.075700,323.075700
XS GIS Cut Line= 6
 463332.29457745743911.999503523463189.295102775744207.877690166
463119.860176921744442.503417701463085.051037699744533.523555502
462980.626286447744738.200371742462871.740163296744911.010364085
#Sta/Elev= 30
9499.038238.56189535.604 236.3849547.843232.75829559.193234.23089570.542234.4106
9581.892233.03049604.464231.57669637.977227.24169666.497225.53659715.746 220.401
9748.759 218.4939759.734 218.1819770.571 219.4279792.244219.34669867.478 221.173
9930.651218.67899951.306218.7532 9982.29217.850410002.93 216.25510013.73217.5495
10171.88218.315510282.84222.016310294.09 221.64410327.83223.693410385.01225.6444
10408.16 227.42510429.44 227.49410504.47 229.756   10550232.456810604.38237.0333
#Mann= 3 , 0 , 0
9499.038    0.04       09499.038    0.04       010604.38    0.04       0
#XS Ineff= 2 , 0
       09869.179         10127.8       0
Bank Sta=9499.038,10604.38
Exp/Cntr=0.3,0.1

Type RM Length L Ch R = 1 ,3227.791,313.850700,313.850700,313.850700
XS GIS Cut Line= 6
463005.318980964743793.397937702 462859.80322825744149.896615603
462837.849976096  744228.1038948462822.354753827744340.781632989
462785.591658585744460.298664993462667.894173108744732.144930338
#Sta/Elev= 30
 9489.51234.76849524.126230.97619556.988228.70689567.942 226.4419578.896225.8564
9600.804223.24229633.395217.98759644.245216.80749676.794214.64569720.127214.5416
9799.238217.67129837.712 216.8879880.067214.87129962.967215.013810003.16213.4119
10013.19214.591210033.45214.578610074.31217.037510189.42 228.29510232.09233.4563
10275.01237.822110285.84240.239810329.19243.029610357.45243.641210372.95246.3303
10395.06248.181210417.17252.805710439.28253.582610461.39255.2133 10491.4255.8449
#Mann= 3 , 0 , 0
 9489.51  0.0465       0 9489.51  0.0465       0 10491.4  0.0465       0
#XS Ineff= 2 , 0
       09799.919                       0
Bank Sta=9489.51,10491.4
Exp/Cntr=0.3,0.1

Type RM Length L Ch R = 1 , 2913.94,728.885000,728.885000,728.885000
XS GIS Cut Line= 6
462723.634953201743699.647937715462634.288058698743905.349074766
462578.119200498744056.146615624462480.166439623744429.612487629
462445.602532119744512.372932076462386.210145324744638.394930348
#Sta/Elev= 30
 9495.61233.24569512.427231.08889523.381230.22439578.151226.53819621.865224.7021
9632.715223.86859643.564220.68299666.504217.35419686.963215.49659708.663214.4975
9805.357211.67629837.182211.74629869.007212.80049920.999213.285810011.38212.5308
10096.75212.904810107.09211.507610127.76212.899910148.44212.231710179.46214.4489
10231.15216.032310272.77218.869410283.61220.592310306.28220.931410337.79222.7032
10358.03223.310110381.63221.3614 10414.8223.306810470.07228.273510495.93229.5903
#Mann= 3 , 0 , 0
 9495.61  0.0465       0 9495.61  0.0465       010495.93  0.0465       0
#XS Ineff= 2 , 0
       0 9802.95        10228.31       0
Bank Sta=9495.61,10495.93
Exp/Cntr=0.3,0.1

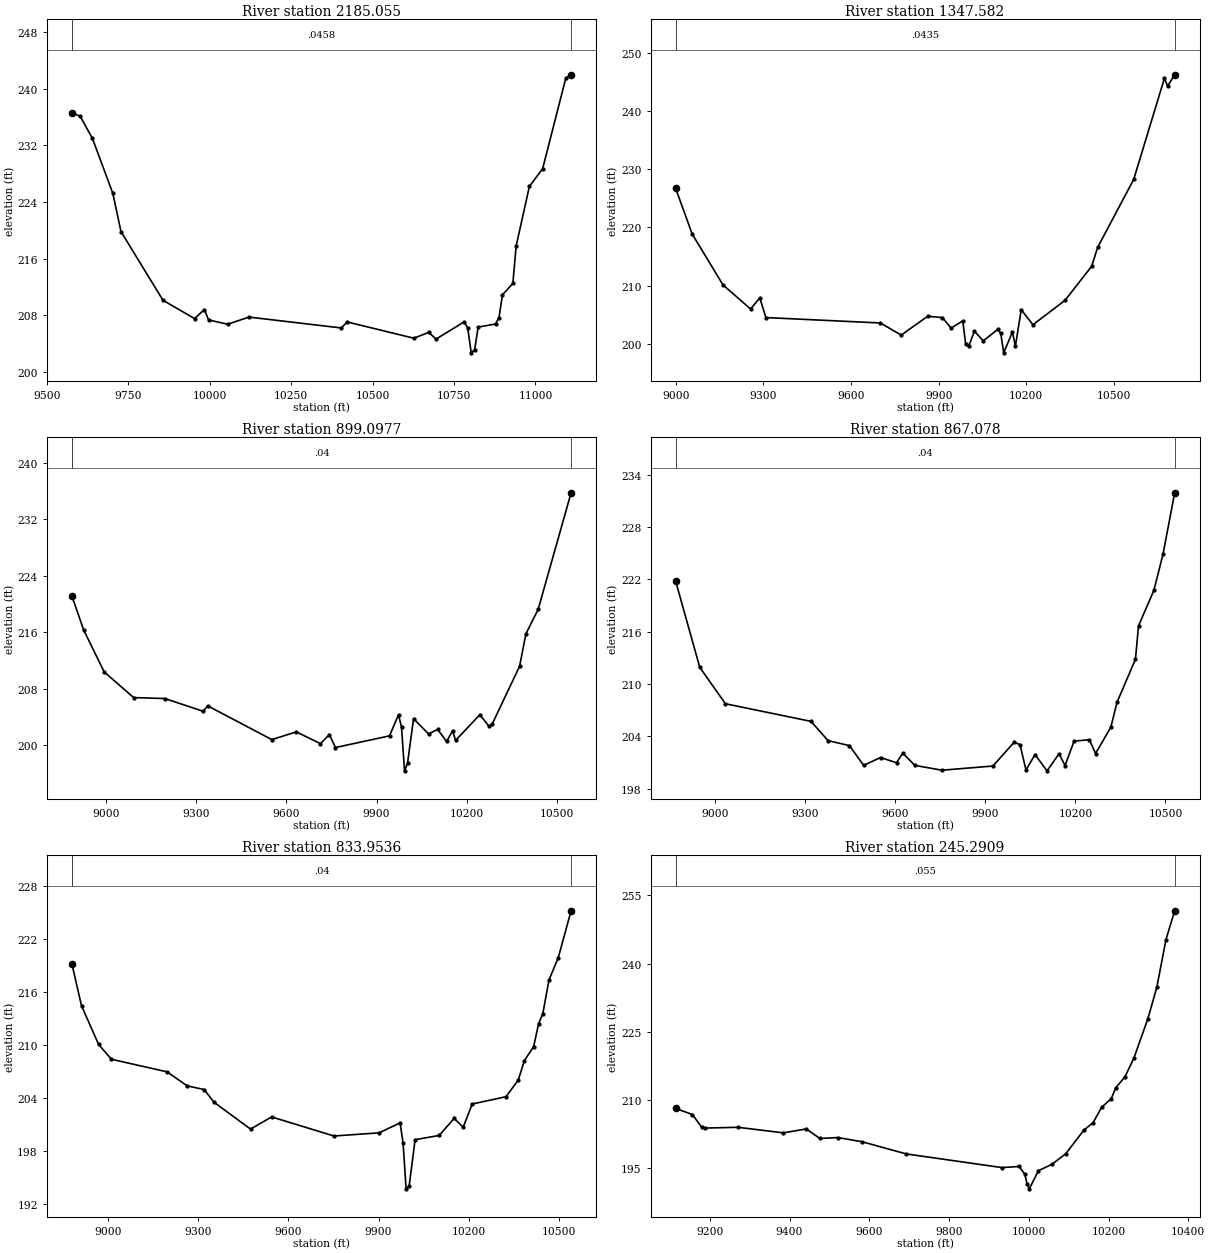
Type RM Length L Ch R = 1 ,2185.055,837.473400,837.473400,837.473400
XS GIS Cut Line= 6
462139.359880139743474.959885086461957.061477919743728.428243424
461891.052882125743863.065737705461564.406090667744205.361587192
461185.933868458744375.500476087461008.850535115744406.750476087
#Sta/Elev= 30
9576.552236.55189601.718236.09499639.392232.96959702.182225.18679727.158219.8113
 9856.06  210.119952.947207.52539983.334208.79229996.048207.331510054.48206.7289
10120.54207.731310404.12206.194610421.48207.049110626.51  204.7510671.95205.5696
10694.66204.6252 10781.4207.069610792.06206.142610802.71 202.68510813.37203.1386
10824.03206.320910877.31206.754810887.97207.673610898.63210.872210930.55212.4836
10940.71217.777610981.32226.181611021.94228.675811093.02241.432211109.42241.9434
#Mann= 3 , 0 , 0
9576.552  0.0458       09576.552  0.0458       011109.42  0.0458       0
#XS Ineff= 2 , 0
       09979.493        10437.59       0
Bank Sta=9576.552,11109.42
Exp/Cntr=0.3,0.1

Type RM Length L Ch R = 1 ,1347.582,448.484100,448.484100,448.484100
XS GIS Cut Line= 6
 461308.61458391 742720.94226931461183.860589385743111.604488328
461106.835571796743440.653689802461089.513322711743614.764987856
461082.958484262744055.515261367460995.998211682744387.743424371
#Sta/Elev= 30
8999.073226.7727 9056.13 218.8729161.676210.13559256.188206.01559287.625207.9159
9308.573204.54079700.744203.61069771.873 201.5339862.517204.7643 9912.61204.5433
9942.628202.73079982.629203.97089992.629199.935610002.63 199.58510022.65202.2243
10052.67200.536710102.72202.529410112.73201.814410122.74198.490210152.76202.0815
10162.77199.614410182.77205.890910222.78203.295610333.14 207.51710424.12213.3536
10444.41216.5831 10567.9228.240210673.15245.593610683.82244.235310708.11246.1803
#Mann= 3 , 0 , 0
8999.073  0.0435       08999.073  0.0435       010708.11  0.0435       0
#XS Ineff= 2 , 0
       09862.906        10190.93       0
Bank Sta=8999.073,10708.11
Exp/Cntr=0.3,0.1

Type RM Length L Ch R = 1 ,899.0977,32.019700,32.019700,32.019700
XS GIS Cut Line= 4
461231.353189155742727.769097224460705.508056775743246.480085582
460691.742145017743837.039636865 460760.43305026744162.230902776
#Sta/Elev= 30
8885.926221.12388924.702216.34088993.175210.38279091.501206.74169195.256206.6088
9323.414204.79699337.653205.58119551.249200.79399633.078201.88889713.099200.2216
9743.108201.50559763.113199.67119943.162201.3228 9973.17204.32369983.173202.5212
9993.176196.370310003.18197.456310023.18203.7622 10073.2201.592110103.21 202.243
10133.21 200.52710153.22202.035710163.22200.674710243.85204.322910274.51202.6705
10284.74202.9716 10376.2211.179410397.16215.768810438.05219.242410547.64235.7435
#Mann= 3 , 0 , 0
8885.926    0.04       08885.926    0.04       010547.64    0.04       0
#XS Ineff= 2 , 0
       09963.903        10126.68       0
Bank Sta=8885.926,10547.64
Exp/Cntr=0.3,0.1

Type RM Length L Ch R = 1 , 867.078,33.124400,33.124400,33.124400
XS GIS Cut Line= 4
461200.845132411742718.264146253 460675.00000003743236.975134611
460661.234088272743827.534685895460729.924993515744152.725951806
#Sta/Elev= 30
 8868.95221.8593 8949.74211.91159035.179207.73579319.973205.71369376.932203.5033
 9448.13202.93249495.208200.66329551.394201.56749604.767200.9671 9625.61  202.07
 9665.62 200.6669755.645200.11059925.691  200.59 9995.71203.294310015.72203.0594
10035.72 200.12910065.73201.900710105.74200.037610145.75201.994410165.76 200.647
10195.76203.446410246.81203.610710267.25202.020610318.36205.0629 10338.8207.9101
10400.12212.837310410.34216.677210461.45220.750110492.11 224.93710530.67231.9476
#Mann= 3 , 0 , 0
 8868.95    0.04       0 8868.95    0.04       010530.67    0.04       0
#XS Ineff= 2 , 0
       09951.967        10110.15       0
Bank Sta=8868.95,10530.67
Exp/Cntr=0.3,0.1

Type RM Length L Ch R = 1 ,833.9536,588.662700,588.662700,588.662700
XS GIS Cut Line= 4
461168.293049077742722.604424031460642.447916696743241.315412389
460628.682004938743831.874963673460697.372910182744157.066229583
#Sta/Elev= 30
8879.301219.13398911.191214.4122 8968.15210.04689010.869208.37529195.986206.9543
9263.183205.36919319.369204.95859352.623203.50949473.881200.48869544.113201.8614
9751.652199.70759901.692200.06389971.711201.18889981.714198.91129991.717193.7387
10001.72 194.01910021.72199.294110101.75199.769510151.76201.697910181.77200.7031
10211.84203.323610324.27204.146310365.15206.0213 10385.6208.234810416.26209.7961
10432.76212.389810446.92213.532610467.36217.337710498.02 219.81710541.02225.1506
#Mann= 3 , 0 , 0
8879.301    0.04       08879.301    0.04       010541.02    0.04       0
#XS Ineff= 2 , 0
       09953.259        10106.59       0
Bank Sta=8879.301,10541.02
Exp/Cntr=0.3,0.1

Type RM Length L Ch R = 1 ,245.2909,0.000000,0.000000,0.000000
XS GIS Cut Line= 2
460590.710583776 742637.86050041 459986.54391712743734.214667097
#Sta/Elev= 30
9114.095208.1682  9156.5206.83159179.336204.08299188.086203.85069270.679204.0245
9384.858202.79949441.947 203.6649476.201201.56289521.872201.76469581.756200.8499
 9693.14198.16269932.915 195.1689975.426195.40889990.005193.72649996.146191.4578
10001.42190.498310024.26194.486710058.51195.908810092.77198.220810138.44203.4202
10161.27205.027610182.62208.398710206.94  210.3310218.36212.7337 10241.2215.1076
10264.03219.302510298.29227.779610321.12234.770410343.96245.2185 10365.9251.5991
#Mann= 3 , 0 , 0
9114.095   0.055       09114.095   0.055       0 10365.9   0.055       0
#XS Ineff= 2 , 0
       09811.911                       0
Bank Sta=9114.095,10365.9
Exp/Cntr=0.3,0.1